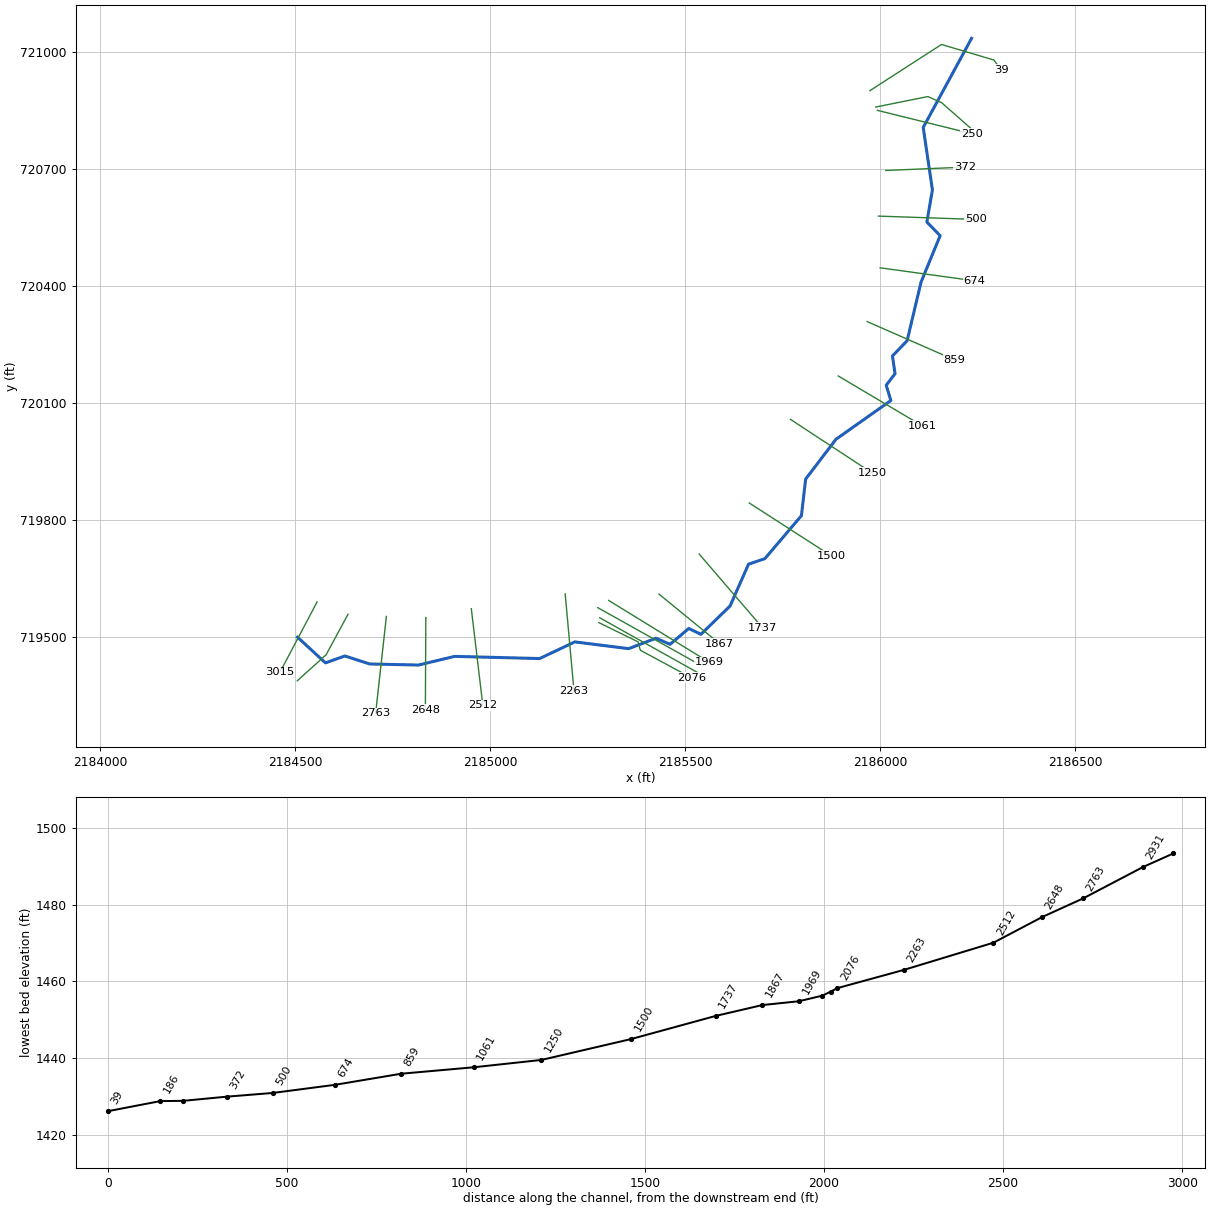
--- RATCLIFFTR.prj (project) ---

Proj Title=RATCLIFFTR
Current Plan=p01
Default Exp/Contr=0.3,0.1
English Units
Geom File=g01
Flow File=f01
Plan File=p01
Y Axis Title=Elevation
X Axis Title(PF)=Main Channel Distance
X Axis Title(XS)=Station
BEGIN DESCRIPTION:
---------- MODELED AS PART OF WVEMD CTP PROGRAM, 2023----------
Stream Name: Ratcliff Run Tributary
Flood Zone:  AFH
Upshur County, WV
HEC-RAS Version: RAS 6.3
Vertical Datum: NAVD88
Projection: NAD 1983 StatePlane West Virginia S FIPS 4702 (US Feet)
Terrain: 1-meter LIDAR (FEMA Region III 3DEP collected 2016-2018)
Land Use: 2019 NLCD
Hydrologic Method:
WV SIR2010-5033 regression equations
Additional Model Notes:
None
END DESCRIPTION:
DSS Export Rating Curves= 0
DSS Export Rating Curve Sorted= 0
DSS Export Volume Flow Curves= 0
DXF OffsetX= 0
DXF OffsetY= 0
DXF ScaleX= 1
DXF ScaleY= 10

--- RATCLIFFTR.p01 (plan) ---

Plan Title=Floodplain
Program Version=6.31
Short Identifier=Floodplain
Geom File=g01
Flow File=f01
Subcritical Flow
K Sum by GR= 0
Std Step Tol= 0.01
Critical Tol= 0.01
Num of Std Step Trials= 20
Max Error Tol= 0.3
Flow Tol Ratio= 0.001
Split Flow NTrial= 30
Split Flow Tol= 0.02
Split Flow Ratio= 0.02
Log Output Level= 0
Friction Slope Method= 1
Unsteady Friction Slope Method= 2
Unsteady Bridges Friction Slope Method= 1
Parabolic Critical Depth
Global Vel Dist= 0 , 0 , 0
Global Log Level= 0
CheckData=True
Encroach Param=-1 ,0,0, 0
Computation Interval=1MIN
Output Interval=1HOUR
Instantaneous Interval=1HOUR
Mapping Interval=1HOUR
Computation Time Step Use Courant=        0
Computation Time Step Use Time Series=    0
Computation Time Step Count To Double=0
Computation Time Step Max Doubling=0
Computation Time Step Max Halving=0
Computation Time Step Residence Courant=0
Run HTab= 0
Run UNet= 0
Run Sediment= 0
Run PostProcess= 0
Run WQNet= 0
Run RASMapper=-1
UNET Theta= 1
UNET Theta Warmup= 1
UNET ZTol= 0.02
UNET ZSATol= 0.02
UNET MxIter= 20
UNET Max Iter WO Improvement= 0
UNET MaxInSteps= 0
UNET DtIC= 0
UNET DtMin= 0
UNET MaxCRTS= 20
UNET WFStab= 2
UNET SFStab= 1
UNET WFX= 1
UNET SFX= 1
UNET Gravity=32.17405
UNET 1D Methodology=Finite Difference
UNET DSS MLevel= 4
UNET Pardiso=0
UNET DZMax Abort= 100
UNET Use Existing IB Tables=-1
UNET Froude Reduction=False
UNET Froude Limit= 0.8
UNET Froude Power= 4
UNET D1 Cores= 0
UNET WindReference=Eulerian
UNET WindDragFormulation=Hsu (1988)
UNET D2 Coriolis=0
UNET D2 Cores= 0
UNET D2 Theta= 1
UNET D2 Theta Warmup= 1
UNET D2 Z Tol= 0.01
UNET D2 Volume Tol= 0.01
UNET D2 Max Iterations= 20
UNET D2 Equation= 0
UNET D2 RampUpFraction=0.1
UNET D2 TimeSlices= 1
UNET D2 Turbulence Formulation=None
UNET D2 Eddy Viscosity=0.3
UNET D2 Transverse Eddy Viscosity=0.1
UNET D2 Smagorinsky Mixing=0.05
UNET D2 BCVolumeCheck=0
UNET D2 Cores=0
UNET D2 SolverType=PARDISO (Direct)
UNET D2 Minimum Iterations= 3
UNET D2 Maximum Iterations= 30
UNET D2 Restart Number= 10
UNET D2 Relaxation Coeff=1.3
UNET D2 SOR Precondition Iterations= 10
UNET D2 ILUT Maximum Fill= 8
UNET D2 ILUT Tolerance=1E-08
UNET D2 Convergence Tolerance=0.00001
UNET D1D2 MaxIter= 0
UNET D1D2 ZTol=0.01
UNET D1D2 QTol=0.1
UNET D1D2 MinQTol=1
Write IC File= 0
Write IC File at Fixed DateTime=0
Write IC File at Sim End=0
Echo Input=False
Echo Parameters=False
Echo Output=False
Write Detailed= 0
HDF Write Warmup=0
HDF Write Time Slices=0
HDF Flush=0
HDF Compression= 1
HDF Chunk Size= 1
HDF Spatial Parts= 1
HDF Use Max Rows=0
HDF Fixed Rows= 1
Calibration Method= 0
Calibration Iterations= 20
Calibration Max Change=0.05
Calibration Tolerance=0.2
Calibration Maximum=1.5
Calibration Minimum=0.5
Calibration Optimization Method= 1
WQ AD Non Conservative
WQ ULTIMATE=-1
WQ Max Comp Step=1HOUR
WQ Output Interval=15MIN
WQ Output Selected Increments= 0
WQ Create Restart=0
WQ Fixed Restart=0
WQ System Summary=0
WQ Write To DSS=0
Sorting and Armoring Iterations= 10
XS Update Threshold= 0.02
Bed Roughness Predictor= 0
Hydraulics Update Threshold= 0.02
Energy Slope Method= 1
Volume Change Method= 1
Sediment Retention Method= 0
Sediment TS Multiplier= 1
Warm Up Method= 0
XS Weighting Method= 0
Number of US Weighted Cross Sections= 1
Number of DS Weighted Cross Sections= 1
Upstream XS Weight=0
Main XS Weight=1
Downstream XS Weight=0
Number of DS XS's Weighted with US Boundary= 1
Upstream Boundary Weight= 1
Weight of XSs Associated with US Boundary= 0
Number of US XS's Weighted with DS Boundary= 1
Downstream Boundary Weight= 0.5
Weight of XSs Associated with DS Boundary= 0.5
Percentile Method= 0
Sediment Output Level= 3
Mass or Volume Output= 0
Output Increment Type= 1
Profile and TS Output Increment= 1
Transport Output Increment 1
XS Output Flag= 0
XS Output Increment= 10
Read HDF5 Sediment Hotstart= 0
Sediment Hotstart Type= 0
Write Gradation File= 0
Read Gradation Hotstart= 0
Write HDF5 File= 1
Write Binary Output= 1
Write DSS Sediment File= 0
DSS Sediment Output Type= 1
SV Curve= 0
Specific Gage Flag= 0
Subcell Erosion Methods= 0
Subcell Deposition Methods= 0
Advection Scheme= 1
Matrix Solver= 0
Implicit Weighting Factor= 1
Maximum Outer Loop Convergence Iterations= 5
Convergence Maximum Absolute= 0.001
Convergence RMSE= 0.0001
Grain Fractions Max Abs Error= 0.001
Max Subgrid Regions= 1
Max Subgrid Length Scale= 3.402823E+38
Initial Layer Thickness= 3.402823E+38
Min Layer Thickness= 3.402823E+38
Max Layer Thickness= 3.402823E+38
Number of Layers= 5

--- RATCLIFFTR.f01 (steady flow) ---

Flow Title=Flow
Program Version=6.31
Number of Profiles= 1
Profile Names=01pct
River Rch & RM=RATCLIFFTR,Main            ,3015
    60.8
Boundary for River Rch & Prof#=RATCLIFFTR,Main            , 1
Up Type= 0
Dn Type= 3
Dn Slope=0.0179
DSS Import GetInterval= 0
DSS Import GetPeak= 0
DSS Import FillOption= 0

--- RATCLIFFTR.g01 (geometry) ---

Geom Title=Geometry
Program Version=6.31

River Reach=RATCLIFFTR      ,Main
Reach XY= 30
2184505.59677893719499.6378335952184577.41404576719433.638769086
2184627.12442301 719451.373822512184690.66596259719430.887643009
2184816.01348092719428.1100895112184908.37451668719450.332157925
2185126.42985484719444.7767228342185216.70788951719487.484970748
2185354.55505475719470.1237850042185424.69402209719496.859952003
2185460.80484226719481.2349832512185508.72174117719521.859902009
2185539.97167867719506.929485679 2185614.6244165719579.498894334
2185661.99474787719686.772497747 2185703.7605581719700.782878167
2185797.61059909719811.0962001682185808.37435709719904.846012667
2185886.15208867720006.9294699282186026.77713551720106.235045582
2186014.97171292720145.4711875922186037.54122159720174.984908089
2186030.94379383720220.4710375822186068.44404693720259.360067427
2186104.20775492720409.7072076652186153.16599034720528.804410428
2186119.13849933720563.8738940952186133.37436326720646.165396169
   2186109.76319720806.2349579192186233.72160351721034.707270011

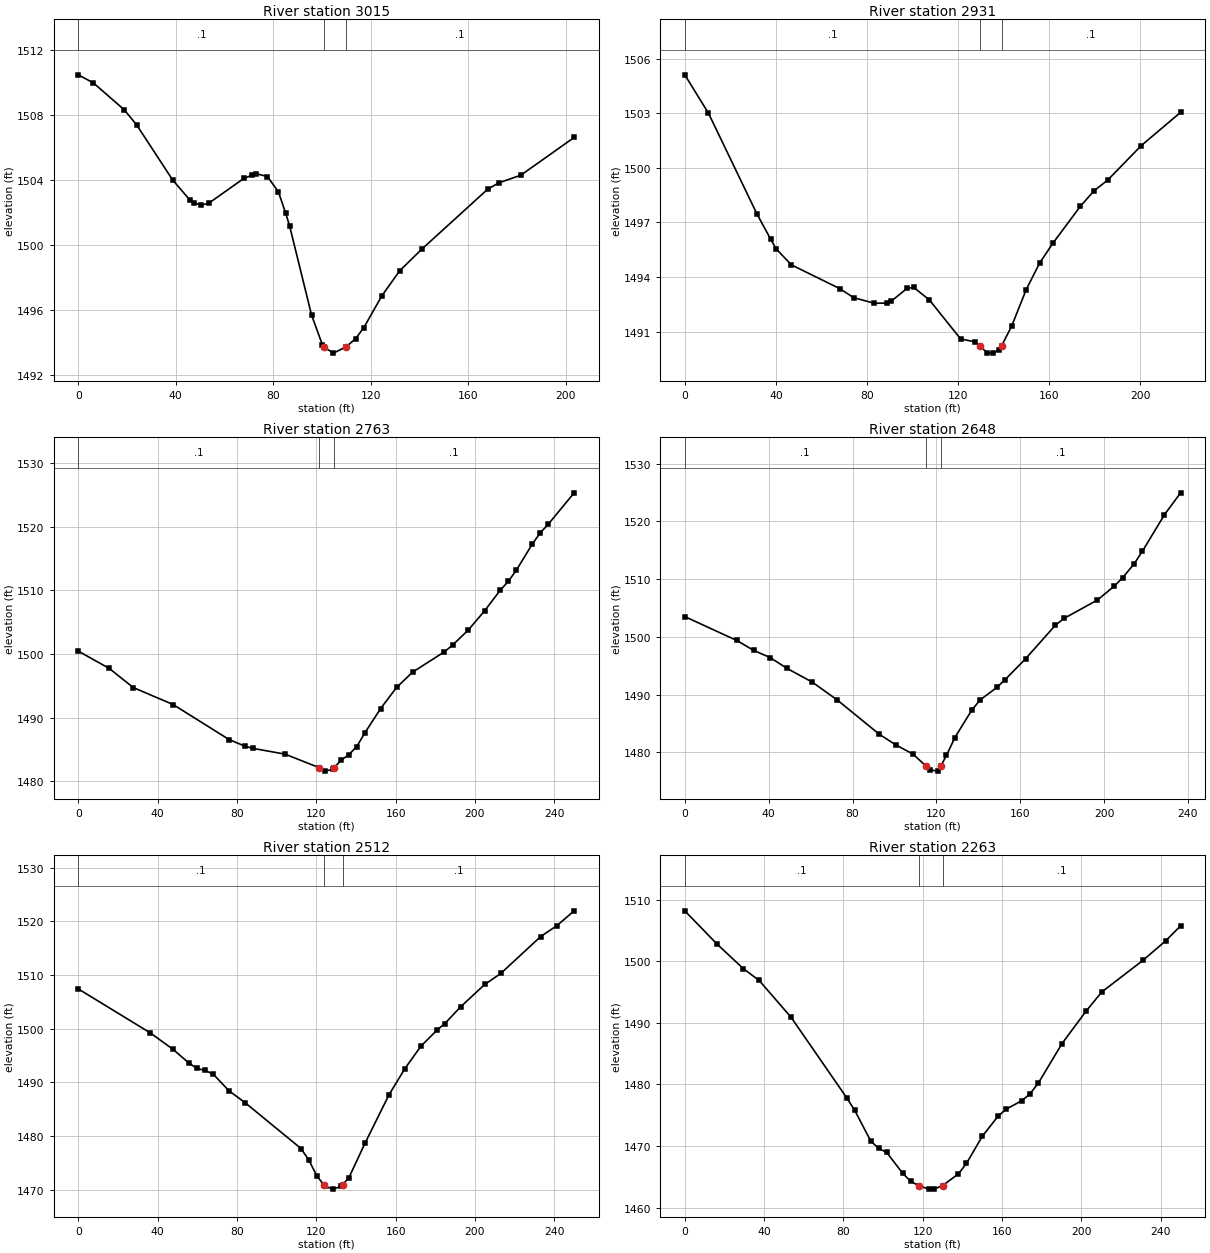
Type RM Length L Ch R = 1 ,3015    ,84.2,84.2,84.2
XS GIS Cut Line= 2
2184555.88327935719589.8154218162184460.88734976719409.823134167
#Sta/Elev= 30
       0 1510.49     6.2 1509.99    18.8 1508.34    23.9 1507.41    38.7 1504.01
    45.9 1502.75    47.6 1502.59    50.5 1502.46    53.5 1502.57    67.9  1504.1
    71.3  1504.3    73.1 1504.39    77.6 1504.22    82.1 1503.28    85.1 1501.96
    86.7 1501.18    95.7 1495.69   100.2 1493.83   100.9 1493.69   104.7 1493.33
   109.8 1493.71   113.8 1494.22   117.2 1494.91   124.6 1496.87   131.9 1498.41
   140.9 1499.73   168.1 1503.45   172.6 1503.83   181.6  1504.3   203.5 1506.63
#Mann= 3 ,-1,0
       0      .1       0   100.9    .045       0   109.8      .1       0
Bank Sta=100.9,109.8
XS Rating Curve= 0 ,0
Exp/Cntr(USF)=0,0
Exp/Cntr=0.3,0.1

Type RM Length L Ch R = 1 ,2931    ,167.7,167.7,167.7
XS GIS Cut Line= 3
2184635.27133141719558.3461843862184579.13523556719454.538959512
 2184505.1781569719387.710273971
#Sta/Elev= 30
       0 1505.11    10.4    1503    31.7 1497.46    37.7 1496.08    40.1 1495.55
    46.8 1494.67    68.1 1493.36    74.1 1492.87    83.2 1492.56    88.7 1492.57
    90.6 1492.67    97.6 1493.38   100.5 1493.43   107.4 1492.74   121.1  1490.6
   127.4 1490.44   129.6 1490.21   132.8 1489.83   135.2 1489.82   137.9 1489.98
  139.11 1490.22   143.6 1491.33   149.9 1493.31   155.8 1494.77   161.8 1495.89
   173.7 1497.89   179.7 1498.74   185.7 1499.33   200.4 1501.22   217.7 1503.05
#Mann= 3 ,-1,0
       0      .1       0   129.6    .045       0  139.11      .1       0
Bank Sta=129.6,139.11
XS Rating Curve= 0 ,0
Exp/Cntr(USF)=0,0
Exp/Cntr=0.3,0.1

Type RM Length L Ch R = 1 ,2763    ,114.9,114.9,114.9
XS GIS Cut Line= 2
2184733.59598171719552.6944872282184706.02085681719304.219916121
#Sta/Elev= 30
       0 1500.47    15.6 1497.75    27.7 1494.75    47.8 1492.08      76 1486.58
    83.9 1485.55    88.1 1485.19   104.2 1484.29   121.51482.157   124.3 1481.62
   128.3 1481.91     1291482.151   132.3 1483.29   136.3 1484.18   140.4 1485.48
   144.4  1487.6   152.4 1491.44   160.5 1494.78   168.5 1497.16   184.6 1500.37
   188.7 1501.42   196.7 1503.81   204.8 1506.79   212.8 1510.06   216.8 1511.43
   220.9 1513.21   228.9 1517.29   232.9 1519.05     237 1520.43     250 1525.34
#Mann= 3 ,-1,0
       0      .1       0   121.5    .045       0     129      .1       0
Bank Sta=121.5,129
XS Rating Curve= 0 ,0
Exp/Cntr(USF)=0,0
Exp/Cntr=0.3,0.1

Type RM Length L Ch R = 1 ,2648    ,135.7,135.7,135.7
XS GIS Cut Line= 2
2184834.73616505719550.0132248312184833.51387542719313.500181353
#Sta/Elev= 30
       0 1503.51    24.8 1499.37    32.8 1497.67    40.8 1496.39    48.8 1494.53
    60.8 1492.16    72.8 1489.04    92.8 1483.12   100.8 1481.25   108.8  1479.7
   114.91477.672   116.8 1476.96   120.8 1476.74   122.1 1477.61   124.8 1479.46
   128.8 1482.54   136.8 1487.26   140.8 1489.05   148.8 1491.23   152.8 1492.59
   162.6 1496.23   176.8 1502.03   180.8 1503.18   196.8 1506.38   204.8 1508.77
   208.8 1510.23   214.3 1512.64   218.3 1514.85   228.8 1521.17   236.5 1524.95
#Mann= 3 ,0,0
       0      .1       0   114.9    .045       0   122.1      .1       0
Bank Sta=114.9,122.1
XS Rating Curve= 0 ,0
Exp/Cntr(USF)=0,0
Exp/Cntr=0.3,0.1

Type RM Length L Ch R = 1 ,2512    ,249.2,249.2,249.2
XS GIS Cut Line= 2
 2184951.2919207719572.6549917832184980.88252967719324.412376866
#Sta/Elev= 30
       0 1507.39    36.3 1499.19    47.8 1496.11    55.9 1493.53    59.9 1492.56
    63.9 1492.19      68 1491.51      76 1488.39    84.1 1486.18   112.3 1477.63
   116.3 1475.44   120.3 1472.51   123.71470.927   124.4 1470.61   128.4 1470.07
   132.4 1470.57   133.31470.932   136.4 1472.18   144.5 1478.59   156.6 1487.63
   164.6 1492.51   172.7  1496.7   180.7 1499.66   184.8 1500.94   192.8 1504.07
   204.9 1508.22     213 1510.27   233.1 1517.15   241.2 1519.16     250 1521.95
#Mann= 3 ,-1,0
       0      .1       0   123.7    .045       0   133.3      .1       0
Bank Sta=123.7,133.3
XS Rating Curve= 0 ,0
Exp/Cntr(USF)=0,0
Exp/Cntr=0.3,0.1

Type RM Length L Ch R = 1 ,2263    ,186.4,186.4,186.4
XS GIS Cut Line= 2
2185191.95613289719610.5712305912185214.46494317719361.586585563
#Sta/Elev= 30
       0 1508.17    16.2 1502.79    29.5 1498.79    37.5 1496.87    53.6 1490.89
    81.7  1477.8    85.7 1475.78    93.8 1470.79    97.8 1469.61   101.8 1468.97
   109.8  1465.6   113.9 1464.26     1181463.575     123 1463.01   125.9 1463.05
     1301463.584     138  1465.5     142 1467.17     150 1471.58     158 1474.86
   162.1    1476   170.1 1477.39   174.1 1478.49   178.3 1480.24   190.2 1486.63
   202.2 1491.84   210.2 1494.99   230.9 1500.11   242.4 1503.28     250 1505.74
#Mann= 3 ,-1,0
       0      .1       0     118    .045       0     130      .1       0
Bank Sta=118,130
XS Rating Curve= 0 ,0
Exp/Cntr(USF)=0,0
Exp/Cntr=0.3,0.1

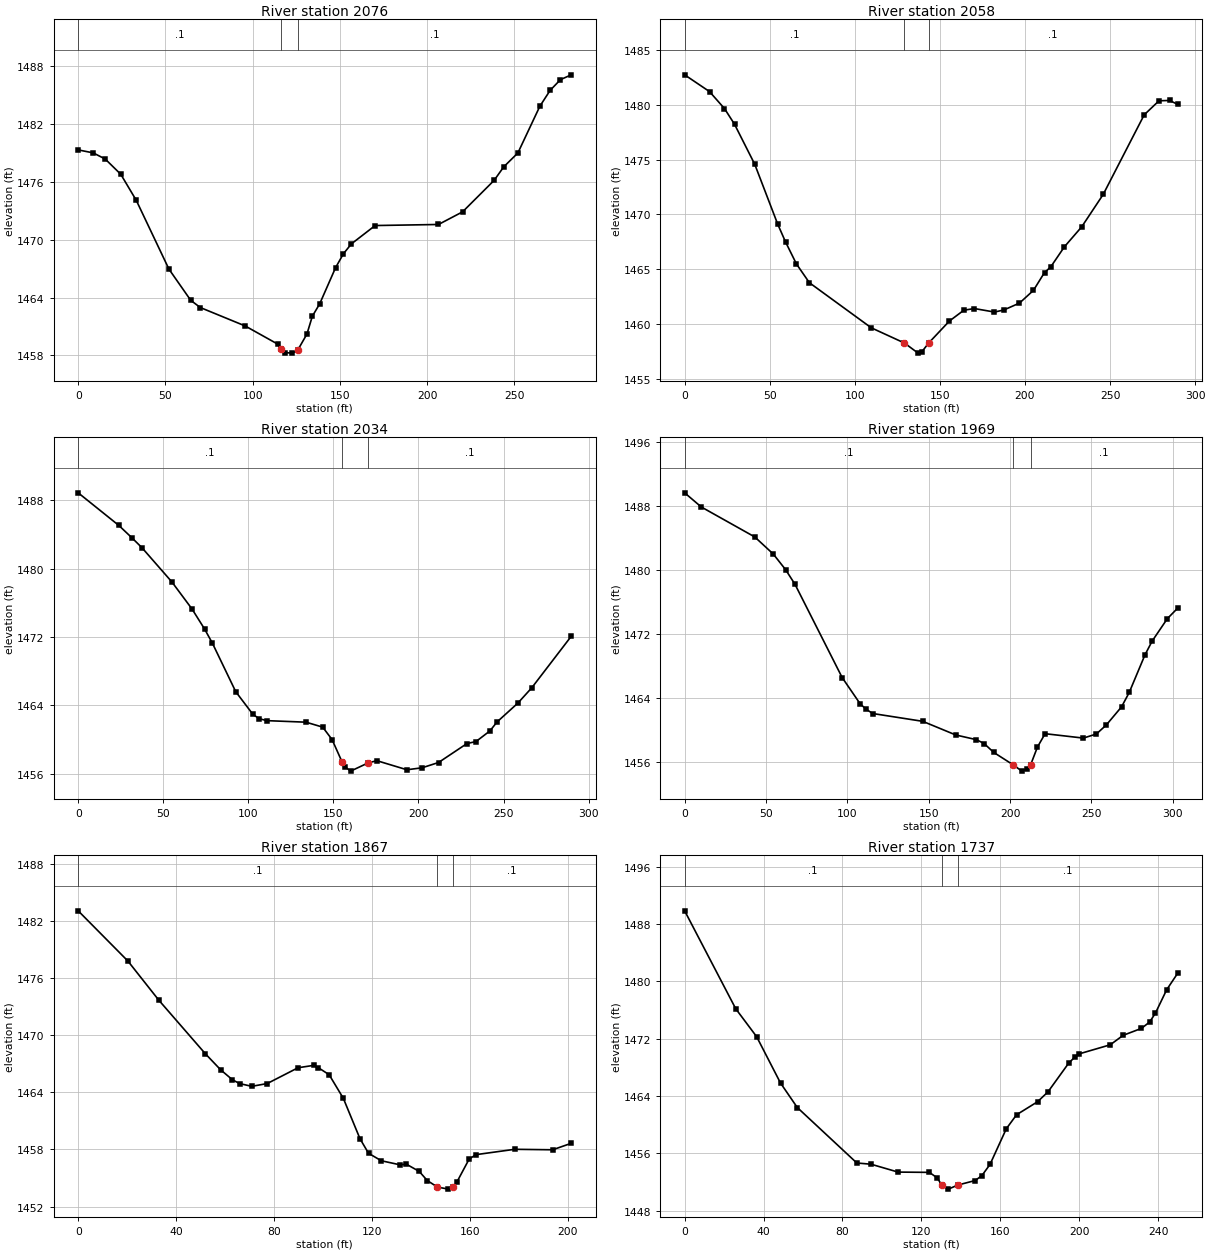
Type RM Length L Ch R = 1 ,2076    ,18.8,18.8,18.8
XS GIS Cut Line= 4
2185278.30015592 719536.951425092185378.99876819719487.455497024
2185384.54572565719466.1210452722185515.11257037719395.717354489
#Sta/Elev= 30
       0 1479.33     8.6 1479.02    15.5 1478.38    24.4  1476.8    33.3 1474.09
      52 1466.96    64.5 1463.72      70 1462.97    95.7 1461.06   114.6 1459.15
   116.5 1458.72   118.7 1458.29   122.8 1458.24     1261458.606   131.1 1460.22
   134.2 1462.07   138.4 1463.35   147.5  1467.1     152 1468.55   156.6 1469.58
   170.2 1471.48   206.5 1471.59   220.3  1472.9   238.4 1476.17   243.9 1477.57
     252 1479.01   264.6 1483.86   270.5 1485.51   276.4 1486.62   282.6 1487.12
#Mann= 3 ,-1,0
       0      .1       0   116.5    .045       0     126      .1       0
Bank Sta=116.5,126
XS Rating Curve= 0 ,0
Exp/Cntr(USF)=0,0
Exp/Cntr=0.3,0.1

Type RM Length L Ch R = 1 ,2058    ,23.2,23.2,23.2
XS GIS Cut Line= 2
 2185280.4600488719549.2717484232185533.38676418719407.781251319
#Sta/Elev= 30
       0 1482.74    14.6 1481.21    23.4 1479.66    29.3 1478.23    41.2 1474.57
    54.7  1469.1    59.3 1467.48    65.7 1465.47    73.3 1463.76   109.7 1459.64
   129.2 1458.25   137.2 1457.33   139.5 1457.47   143.4 1458.25   155.6 1460.26
   164.1 1461.25   170.3  1461.4   182.1 1461.08   187.6 1461.27   196.8  1461.9
     205 1463.06   211.5 1464.69   215.1 1465.19   223.2 1467.04   233.4 1468.87
     246 1471.82   270.1 1479.09   278.8 1480.37     285  1480.4   289.8 1480.04
#Mann= 3 ,-1,0
       0      .1       0   129.2    .045       0   143.4      .1       0
Bank Sta=129.2,143.4
XS Rating Curve= 0 ,0
Exp/Cntr(USF)=0,0
Exp/Cntr=0.3,0.1

Type RM Length L Ch R = 1 ,2034    ,65.7,65.7,65.7
XS GIS Cut Line= 2
2185275.32357641719575.3251332292185528.25029178719433.834636125
#Sta/Elev= 30
       0 1488.86    23.9 1485.04    31.6 1483.59    37.5 1482.43    55.1 1478.42
    66.9 1475.26    74.3 1472.91    78.9 1471.25    92.6 1465.58   102.7 1462.92
   106.4 1462.42   110.9 1462.19   133.9 1462.01   143.7 1461.43   149.2 1459.98
     155  1457.4   156.8  1456.8   160.1 1456.28   170.6 1457.26   175.6  1457.5
   193.2 1456.44   202.1 1456.67   211.8 1457.29   228.5 1459.51   233.8 1459.74
     242 1460.99   246.2 1462.04   258.4 1464.24   266.6 1466.04   289.8 1472.07
#Mann= 3 ,-1,0
       0      .1       0     155    .045       0   170.6      .1       0
Bank Sta=155,170.6
XS Rating Curve= 0 ,0
Exp/Cntr(USF)=0,0
Exp/Cntr=0.3,0.1

Type RM Length L Ch R = 1 ,1969    ,101.7,101.7,101.7
XS GIS Cut Line= 2
2185303.47480899719593.7010667512185561.62167519719434.972745713
#Sta/Elev= 30
       0 1489.69    10.2 1487.92    43.1 1484.16    54.5 1482.01      62 1480.07
    67.8 1478.23    96.8 1466.54   107.9 1463.24   111.4  1462.6   115.5 1462.04
   146.3 1461.06   166.6 1459.35   179.3 1458.76     184 1458.28   189.9 1457.17
     2021455.592   207.2 1454.82   210.2 1455.04   212.61455.608   216.8 1457.84
   221.5 1459.51     245 1458.96     253 1459.47   259.1  1460.6   268.5 1462.88
   273.2 1464.68   282.9  1469.4   287.3 1471.12   296.6 1473.92     303 1475.25
#Mann= 3 ,-1,0
       0      .1       0     202    .045       0   212.6      .1       0
Bank Sta=202,212.6
XS Rating Curve= 0 ,0
Exp/Cntr(USF)=0,0
Exp/Cntr=0.3,0.1

Type RM Length L Ch R = 1 ,1867    ,130.3,130.3,130.3
XS GIS Cut Line= 2
2185432.31478763719610.0270345372185588.24838723719482.607007439
#Sta/Elev= 30
       0 1483.04    20.3 1477.77    32.9 1473.67    51.9 1468.05    58.2 1466.35
      63 1465.31    65.9 1464.91    70.9 1464.62    77.2 1464.91    89.8 1466.57
    96.2 1466.82      98 1466.59   102.5 1465.84   108.3 1463.36   115.1 1459.12
   118.6 1457.59   123.8 1456.81   131.3 1456.39   134.1 1456.44   139.3 1455.69
   142.6 1454.73   146.7 1454.05   151.2 1453.83   153.1 1454.05   154.8 1454.63
   159.7 1456.99   162.5 1457.45   178.3 1458.01   193.8 1457.96   201.4 1458.64
#Mann= 3 ,-1,0
       0      .1       0   146.7    .045       0   153.1      .1       0
Bank Sta=146.7,153.1
XS Rating Curve= 0 ,0
Exp/Cntr(USF)=0,0
Exp/Cntr=0.3,0.1

Type RM Length L Ch R = 1 ,1737    ,236.7,236.7,236.7
XS GIS Cut Line= 2
2185535.27754498719712.8656495942185698.20115553719523.245246877
#Sta/Elev= 30
       0 1489.87    25.9 1476.19    36.5 1472.29    48.6 1465.82    57.1  1462.4
    87.3 1454.65    94.5 1454.48   108.2 1453.38   124.1 1453.34   128.1 1452.56
   130.3 1451.58   133.7    1451   138.5 1451.57   147.3  1452.2   150.7 1452.89
   154.8 1454.44   163.1 1459.44   168.3 1461.39   178.9  1463.2   184.2 1464.58
   194.7 1468.59   197.8 1469.44     200 1469.89   215.8 1471.16   222.3 1472.48
   231.6 1473.45   235.8 1474.35   238.7 1475.59   244.4 1478.85     250 1481.16
#Mann= 3 ,-1,0
       0      .1       0   130.3    .045       0   138.5      .1       0
Bank Sta=130.3,138.5
XS Rating Curve= 0 ,0
Exp/Cntr(USF)=0,0
Exp/Cntr=0.3,0.1

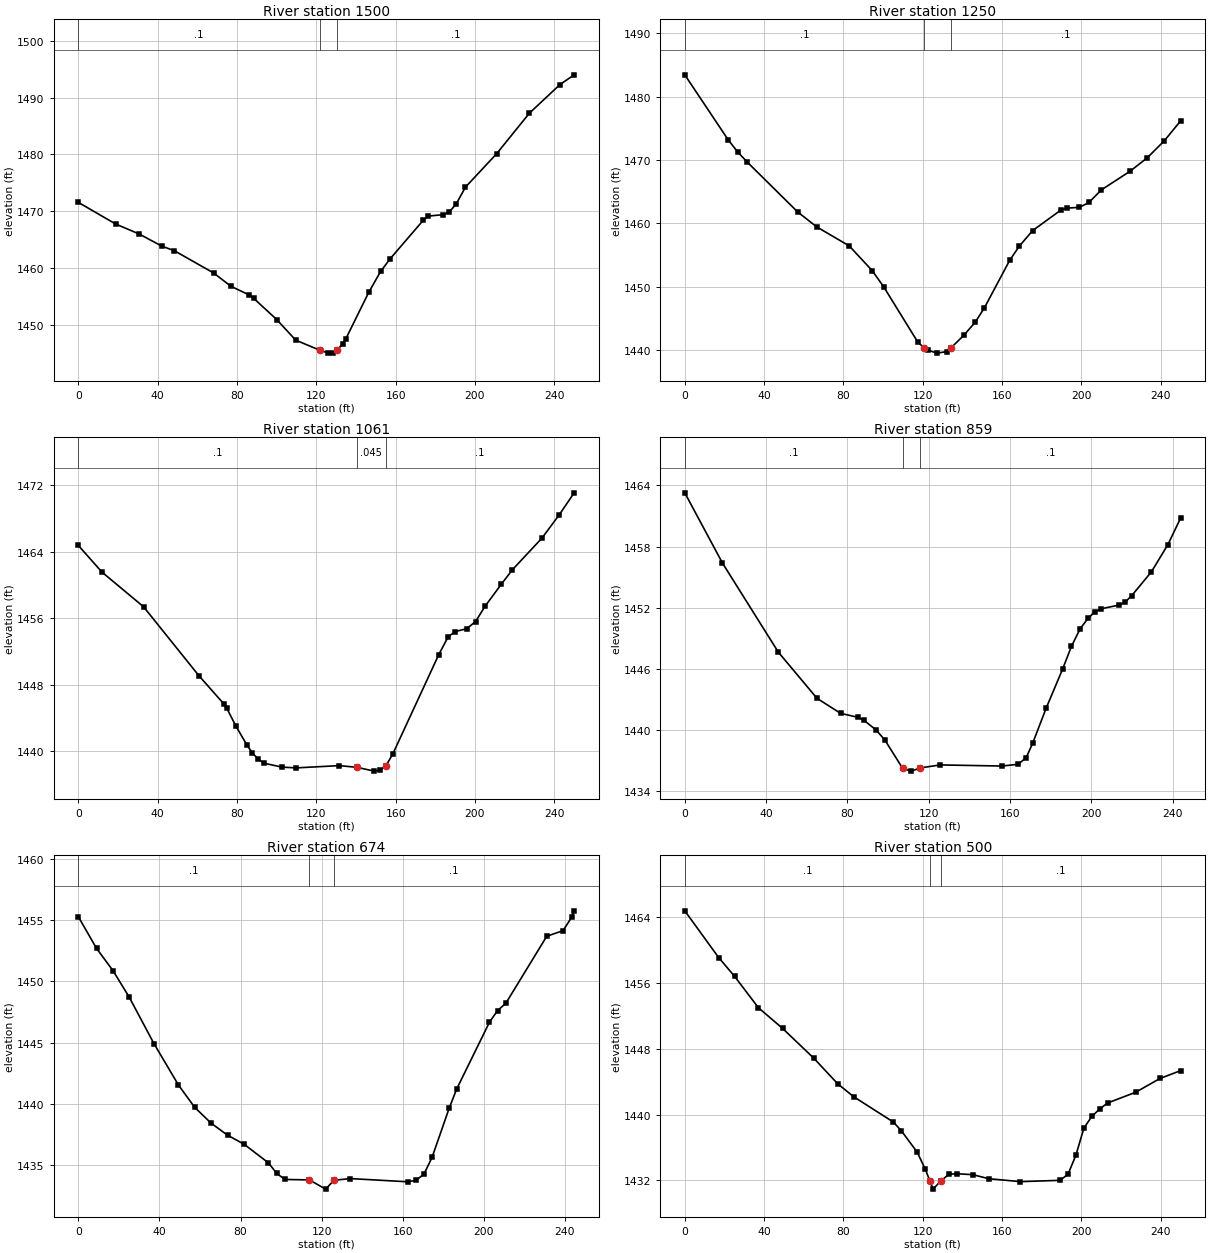
Type RM Length L Ch R = 1 ,1500    ,250,250,250
XS GIS Cut Line= 2
2185664.06711252719843.4146193642185874.20204537719707.977143024
#Sta/Elev= 30
       0 1471.53    18.9  1467.7    30.6 1465.97    42.2  1463.8    48.4 1463.01
    68.3 1459.07    76.9 1456.75    85.8 1455.27    88.5 1454.59   100.1 1450.85
   109.6 1447.25   121.71445.479   126.1 1444.96   128.6 1444.97   130.41445.482
   133.4 1446.62   134.8 1447.43   146.4 1455.65   152.4 1459.35   157.2 1461.58
   173.9 1468.37   176.2  1469.1     184 1469.37   186.9 1469.79   190.5 1471.23
   195.2 1474.22   210.9  1480.1   227.4 1487.24   242.8 1492.28     250 1494.01
#Mann= 3 ,-1,0
       0      .1       0   121.7    .045       0   130.4      .1       0
Bank Sta=121.7,130.4
XS Rating Curve= 0 ,0
Exp/Cntr(USF)=0,0
Exp/Cntr=0.3,0.1

Type RM Length L Ch R = 1 ,1250    ,188.8,188.8,188.8
XS GIS Cut Line= 2
2185769.83732514720057.6970168662185978.82704707719920.498998928
#Sta/Elev= 30
       0 1483.46    21.9 1473.19    26.7 1471.27    31.5 1469.68    56.9 1461.82
    66.5 1459.46    82.9 1456.46    94.5 1452.55   100.3 1449.99   117.6 1441.21
   120.81440.355   122.4 1440.01   127.2 1439.53     132 1439.77   134.21440.355
   140.7 1442.35   146.5 1444.44   151.1  1446.7   163.8 1454.17   168.6 1456.39
   175.4 1458.88   189.8 1462.15   192.7 1462.42     199 1462.54   203.8 1463.32
     210 1465.29   224.5 1468.24   233.2 1470.37   241.8 1473.06     250 1476.19
#Mann= 3 ,-1,0
       0      .1       0   120.8    .045       0   134.2      .1       0
Bank Sta=120.8,134.2
XS Rating Curve= 0 ,0
Exp/Cntr(USF)=0,0
Exp/Cntr=0.3,0.1

Type RM Length L Ch R = 1 ,1061    ,202.7,202.7,202.7
XS GIS Cut Line= 2
2185891.89260026  720169.23283812186106.88189024720041.641281988
#Sta/Elev= 30
       0 1464.73    11.9 1461.53    32.9 1457.36    60.8 1449.08    73.2 1445.74
    74.8  1445.2    79.4 1443.05    84.9  1440.8    87.8 1439.77    90.7 1439.08
    93.4 1438.58   102.7  1438.1   109.8 1438.01   131.6 1438.28   140.4 1438.08
   149.2 1437.62     152 1437.72     155 1438.23   158.5 1439.65   181.7  1451.6
   186.4 1453.73     190 1454.39   195.8 1454.72   200.3 1455.59     205  1457.4
   213.3 1460.08   218.9 1461.82   233.8 1465.62   242.5 1468.42     250 1471.05
#Mann= 3 ,-1,0
       0      .1       0   140.4    .045       0     155      .1       0
Bank Sta=140.4,155
XS Rating Curve= 0 ,0
Exp/Cntr(USF)=0,0
Exp/Cntr=0.3,0.1

Type RM Length L Ch R = 1 ,859     ,184.1,184.1,184.1
XS GIS Cut Line= 2
  2185966.040933720308.6240949722186189.42699461720210.611411234
#Sta/Elev= 30
       0 1463.28    18.5 1456.39      46 1447.63      65  1443.1    76.6 1441.62
    85.3 1441.22    88.2 1440.92    94.1 1439.98    98.4    1439   107.2  1436.2
   111.5 1435.94   115.9 1436.26   125.7 1436.55     156 1436.44   163.9 1436.61
   167.9 1437.25   171.2 1438.72   177.8 1442.15   185.8 1445.94   190.2  1448.2
   194.5 1449.93   198.5 1450.99   201.6 1451.56   204.6 1451.88   213.7 1452.26
   216.4 1452.51   219.8 1453.17   229.5 1455.51   237.6 1458.18   243.9  1460.8
#Mann= 3 ,-1,0
       0      .1       0   107.2    .045       0   115.9      .1       0
Bank Sta=107.2,115.9
XS Rating Curve= 0 ,0
Exp/Cntr(USF)=0,0
Exp/Cntr=0.3,0.1

Type RM Length L Ch R = 1 ,674     ,174.4,174.4,174.4
XS GIS Cut Line= 2
2185999.27026839720446.4620121532186241.58749817720413.099495009
#Sta/Elev= 30
       0 1455.28       9 1452.69    17.1 1450.88    25.1 1448.72    37.3 1444.93
    49.4 1441.55    57.4 1439.73    65.5 1438.44    73.6 1437.46    81.7 1436.73
    93.8  1435.2    97.9 1434.34   101.9 1433.85     114 1433.81     122 1433.06
   126.1 1433.78   134.2 1433.92   162.4 1433.66   166.5 1433.77   170.5 1434.28
   174.5 1435.65   182.9 1439.64   186.6 1441.21   202.8 1446.67   206.8 1447.62
   210.9 1448.22   231.1 1453.69   239.1 1454.14   243.3 1455.22   244.6 1455.76
#Mann= 3 ,-1,0
       0      .1       0     114    .045       0   126.1      .1       0
Bank Sta=114,126.1
XS Rating Curve= 0 ,0
Exp/Cntr(USF)=0,0
Exp/Cntr=0.3,0.1

Type RM Length L Ch R = 1 ,500     ,127.9,127.9,127.9
XS GIS Cut Line= 2
2185995.07875665720578.9905881542186244.93231686720570.434978928
#Sta/Elev= 30
       0 1464.78    17.1 1459.09    25.1 1456.81    37.1    1453    49.3 1450.48
    65.1 1446.84    77.1 1443.74    85.1 1442.18   105.2 1439.08   109.2 1438.02
   117.2 1435.42   121.2 1433.37   123.6 1431.93   125.2 1430.93   129.2 1431.96
   133.2 1432.73   137.2  1432.8   145.2 1432.69   153.2  1432.2   169.2 1431.84
   189.2    1432   193.2 1432.73   197.2 1435.05   201.2 1438.34   205.2 1439.77
   209.2 1440.68   213.2 1441.41   227.3 1442.71   239.6 1444.39     250 1445.34
#Mann= 3 ,-1,0
       0      .1       0   123.6    .045       0   129.2      .1       0
Bank Sta=123.6,129.2
XS Rating Curve= 0 ,0
Exp/Cntr(USF)=0,0
Exp/Cntr=0.3,0.1

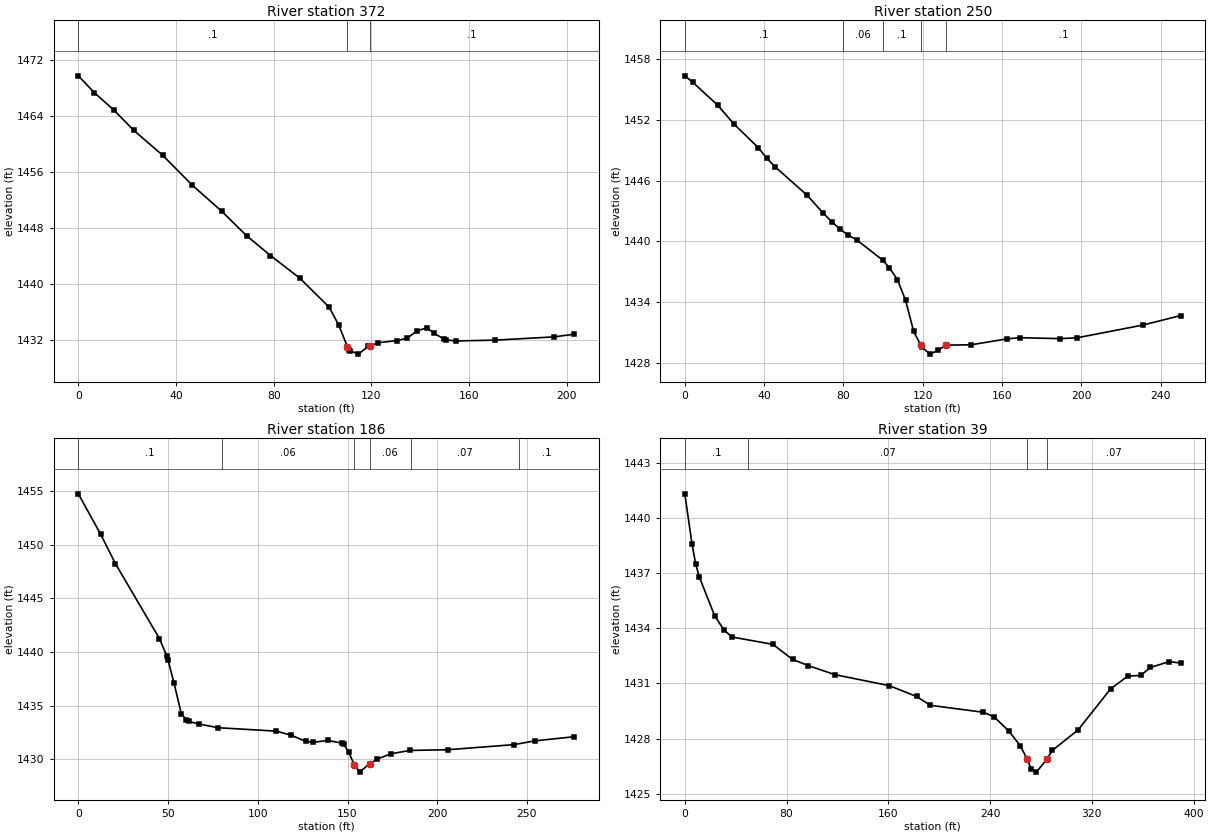
Type RM Length L Ch R = 1 ,372     ,122.1,122.1,122.1
XS GIS Cut Line= 2
2186013.57500088720695.9964900352186216.47507952720704.552517448
#Sta/Elev= 30
       0  1469.7     6.6 1467.28    14.6  1464.8    22.6 1461.95    34.6 1458.34
    46.6 1454.11    58.7 1450.38    68.9 1446.88    78.7 1444.05    90.7 1440.82
   102.7 1436.69   106.7  1434.1   110.21431.037   110.7  1430.6   111.2 1430.48
   114.7 1429.97   118.7 1431.06   119.51431.166   122.7 1431.59   130.7 1431.91
   134.7 1432.26   138.7 1433.27   142.7 1433.74   145.8 1432.93   149.6 1432.16
   150.7 1431.99   154.7 1431.85   170.8 1431.97   194.8 1432.43   203.1 1432.81
#Mann= 3 ,-1,0
       0      .1       0   110.2    .045       0   119.5      .1       0
Bank Sta=110.2,119.5
XS Rating Curve= 0 ,0
Exp/Cntr(USF)=0,0
Exp/Cntr=0.3,0.1

Type RM Length L Ch R = 1 ,250     ,63.9,63.9,63.9
XS GIS Cut Line= 2
2185992.13515537720850.112278126 2186234.8291627720790.115454793
#Sta/Elev= 30
       0 1456.33     4.1 1455.68    16.5 1453.45    24.8 1451.57    37.1 1449.24
    41.2 1448.23    45.4 1447.38    61.8 1444.53    69.9 1442.76    74.2 1441.92
    78.3  1441.2    82.4 1440.62    86.6 1440.16    99.9 1438.13   103.2 1437.38
   107.2 1436.23   111.3  1434.2   115.4 1431.12     119 1429.75   119.5 1429.56
   123.7 1428.88   127.8 1429.27   131.71429.766   144.3  1429.8   162.7 1430.39
     169  1430.5   189.1 1430.41   197.8 1430.49   230.8 1431.74     250 1432.68
#Mann= 5 ,-1,0
       0      .1       0      80     .06       0     100      .1       0
     119    .045       0   131.7      .1       0
Bank Sta=119,131.7
XS Rating Curve= 0 ,0
Exp/Cntr(USF)=0,0
Exp/Cntr=0.3,0.1

Type RM Length L Ch R = 1 ,186     ,147,147,147
XS GIS Cut Line= 4
2185987.90691864720858.5610108752186121.74763316720885.451382743
2186157.19403245720869.5616175482186232.97598953720802.946832693
#Sta/Elev= 30
       0 1454.75    12.5 1450.96    20.7 1448.23    45.2 1441.26    49.2 1439.68
      50 1439.24    53.3 1437.14    57.4 1434.23    60.2 1433.71    61.5 1433.54
      67  1433.3    77.8 1432.95   110.4 1432.63   118.6 1432.25   126.8 1431.67
   130.8 1431.59   139.2 1431.76     147 1431.51   147.9 1431.42   150.7 1430.66
   153.7 1429.52   156.7 1428.81   162.31429.584   166.5 1430.02   174.2 1430.52
   184.7 1430.83     206  1430.9   242.6 1431.37   254.7 1431.73   276.3 1432.11
#Mann= 6 ,-1,0
       0      .1       0      80     .06       0   153.7    .045       0
   162.3     .06       0  185.36     .07       0  245.36      .1       0
Bank Sta=153.7,162.3
XS Rating Curve= 0 ,0
Exp/Cntr(USF)=0,0
Exp/Cntr=0.3,0.1

Type RM Length L Ch R = 1 ,39      ,,,
XS GIS Cut Line= 4
2185973.01646897720900.5190033112186156.59562975 721018.93153559
2186290.90246167720979.1957865032186309.36909143720953.899602044
#Sta/Elev= 30
       0 1441.33     5.7 1438.59     8.6 1437.49    11.4  1436.8    23.4  1434.7
    30.7 1433.92    37.1 1433.53    69.3 1433.13    84.7 1432.31    97.2 1431.97
     118 1431.48   160.8 1430.88   182.2 1430.29   193.1 1429.81   234.7 1429.43
     243 1429.19   254.9  1428.4   263.9 1427.59   269.11426.887   272.2 1426.35
   276.4 1426.17   284.91426.892   288.9 1427.35   309.2 1428.47   334.8 1430.71
   348.3  1431.4   358.5 1431.44     366 1431.87   380.8 1432.19   389.8 1432.11
#Mann= 4 ,-1,0
       0      .1       0      50     .07       0   269.1    .045       0
   284.9     .07       0
Bank Sta=269.1,284.9
XS Rating Curve= 0 ,0
Exp/Cntr(USF)=0,0
Exp/Cntr=0.3,0.1
LCMann Table=0

Chan Stop Cuts=-1
Use User Specified Reach Order=0
Composite Channel Slope=5